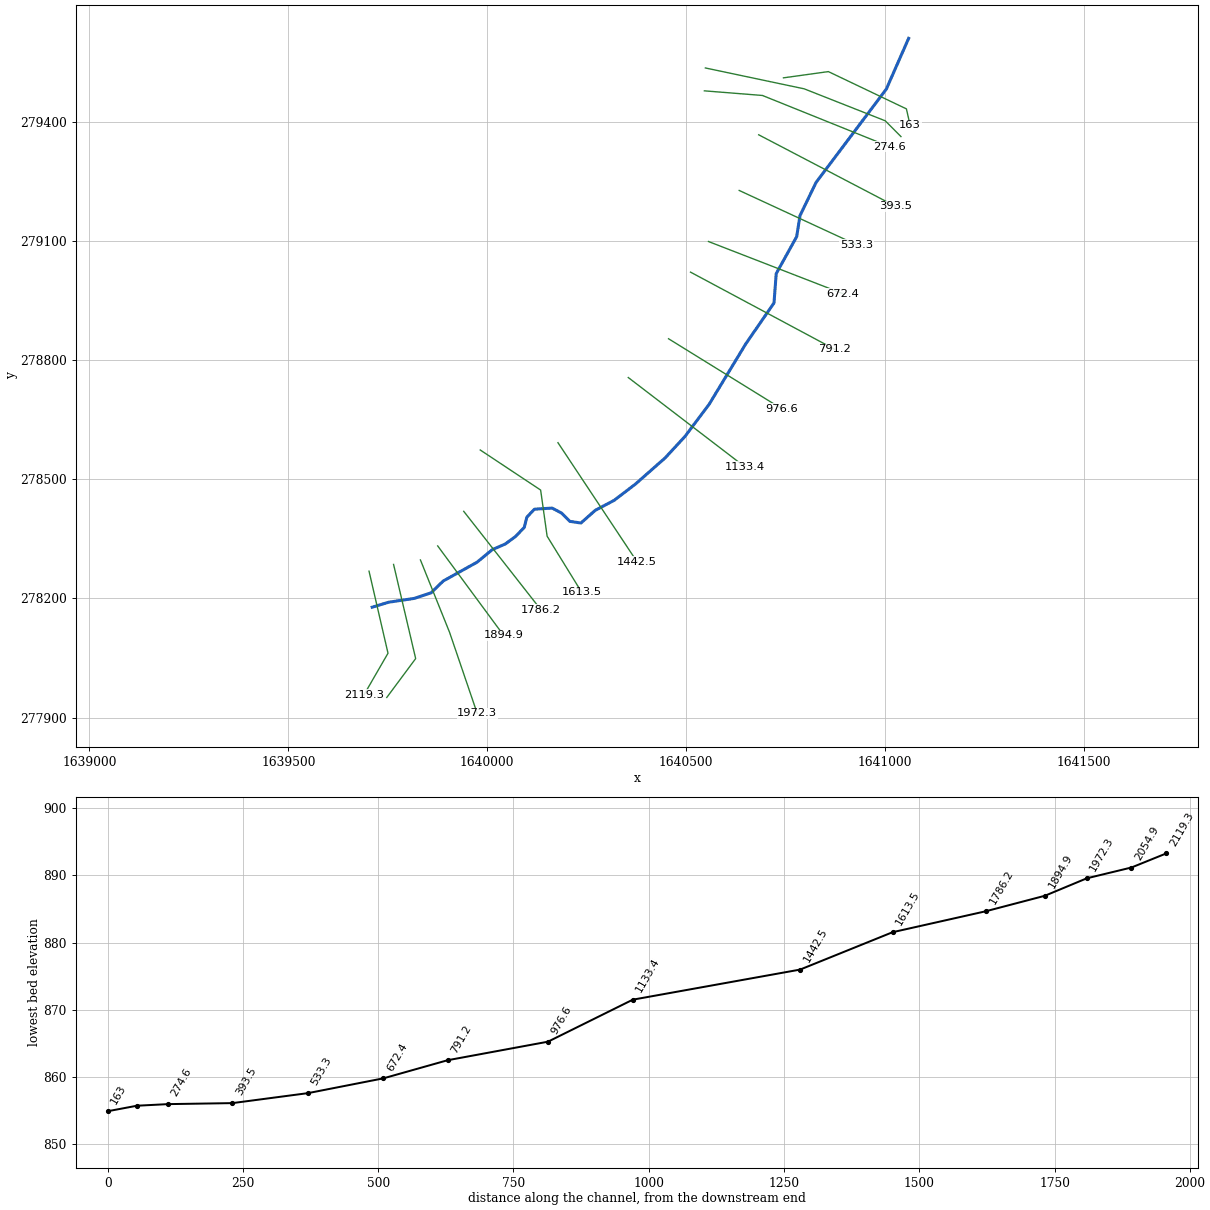
--- BLLICKRN.prj (project) ---

Proj Title=BLLICKRN
Current Plan=p01
Geom File=g01
Flow File=f01
Plan File=p01
DSS Export Rating Curves=0
DSS Export Rating Curve Sorted=0
DSS Export Volume Flow Curves=0
DXF OffsetX=0
DXF OffsetY=0
DXF ScaleX=0
DXF ScaleY=0

--- BLLICKRN.p01 (plan) ---

Plan Title=Floodplain
Program Version=4.00
Geom File=g01
Flow File=f01
K Sum by GR=0
Std Step Tol=0.01
Critical Tol=0.01
Num of Std Step Trials=20
Max Error Tol=0.3
Flow Tol Ratio=0.001
Split Flow NTrial=30
Split Flow Tol=0.02
Split Flow Ratio=0.02
Log Output Level=0
Friction Slope Method=1
Unsteady Friction Slope Method=2
Unsteady Bridges Friction Slope Method=1
Global Log Level=0
CheckData=False
Run HTab=0
Run UNet=0
Run PostProcess=0
UNET Theta=0
UNET Theta Warmup=0
UNET ZTol=0
UNET ZSATol=0
UNET MxIter=0
UNET MaxInSteps=0
UNET DtIC=0
UNET DtMin=0
UNET MaxCRTS=0
UNET WFStab=0
UNET SFStab=0
UNET WFX=0
UNET SFX=0
UNET DSS MLevel=0
UNET DZMax Abort=0
UNET Convert EG Bridges=0
UNET Use Existing IB Tables=0
UNET Froude Limit=0
UNET Froude Power=0
Write IC File=0
Echo Input=False
Echo Output=False
Write Detailed=0

--- BLLICKRN.f01 (steady flow) ---

Flow Title=NFF Regression Equation
Program Version=4.10
Number of Profiles= 1
Profile Names=P100yr
River Rch & RM=BLLICKRN,Main            ,2119.3
257.4912
River Rch & RM=BLLICKRN,Main            ,2054.9
  257.87
River Rch & RM=BLLICKRN,Main            ,1786.2
339.5748
River Rch & RM=BLLICKRN,Main            ,533.3
366.5737
River Rch & RM=BLLICKRN,Main            ,274.6
  371.35
Boundary for River Rch & Prof#=BLLICKRN,Main            , 1
Up Type= 0
Dn Type= 3
Dn Slope=0.01575
DSS Import GetInterval= 0
DSS Import GetPeak= 0
DSS Import FillOption= 0

--- BLLICKRN.g01 (geometry) ---

Geom Title=USGS 10m DEM
Program Version=4.10

River Reach=BLLICKRN        ,Main
Reach XY= 30
     1639710.778      278177.955     1639752.269      278190.551
     1639816.729      278200.182     1639858.961       278214.26
     1639889.338      278243.897     1639974.544      278291.315
      1640012.56      278322.703     1640045.672      278337.252
     1640070.863      278355.775      1640093.09      278378.743
     1640099.689      278404.632     1640118.678      278424.694
     1640163.208      278427.477     1640186.865      278414.953
     1640207.738       278394.08     1640235.569      278389.905
     1640271.749      278421.911     1640319.062      278446.959
     1640371.941      278487.314     1640447.085      278553.552
     1640497.181      278607.822     1640558.131      278689.089
     1640649.974      278840.769     1640720.943      278943.744
     1640726.509      279017.496     1640777.997       279110.73
     1640786.346      279163.609     1640826.701      279247.103
     1641003.428      279482.275     1641059.467      279609.812

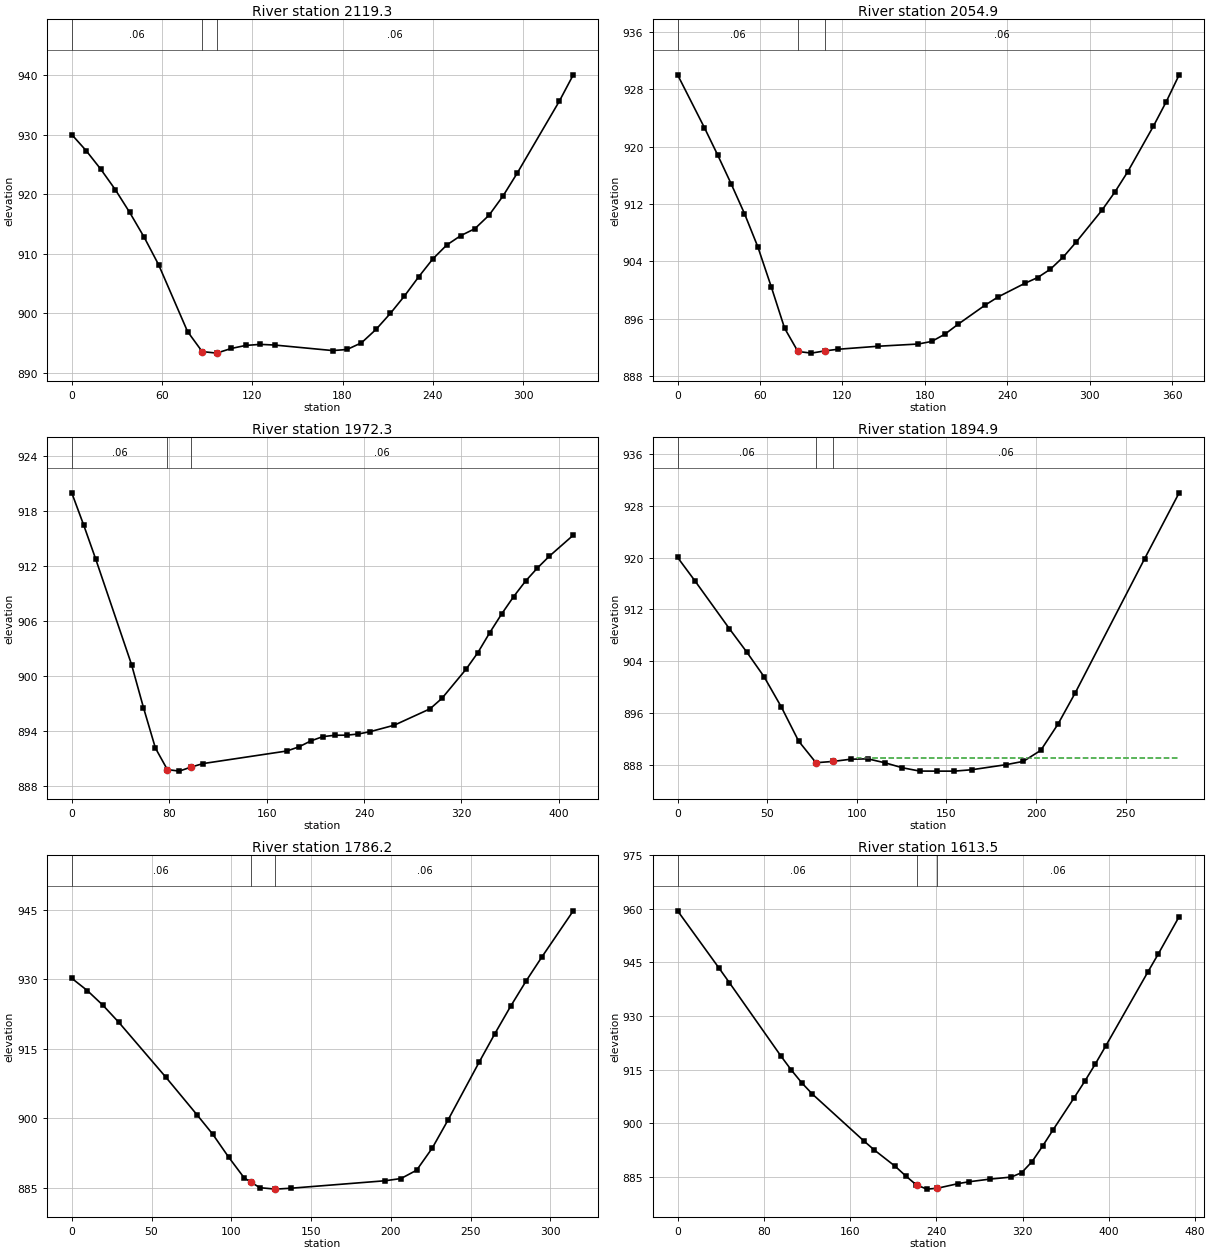
Type RM Length L Ch R = 1 ,2119.3  ,64.2,64.4,64.4
XS GIS Cut Line= 3
     1639702.907      278268.616     1639750.595      278062.156
     1639689.854      277956.871
#Sta/Elev= 30
       0     930     9.6  927.29    19.3  924.18    28.9  920.77    38.5  916.93
    48.2  912.73    57.8  908.11      77  896.91    86.7  893.55    96.3  893.29
     106  894.07   115.6  894.58   125.2  894.76   134.8  894.65   173.4  893.72
     183   893.9   192.6  895.02   202.3  897.28   211.9  899.99   221.2  902.89
   230.6  906.09     240   909.1   249.3  911.45   258.6  913.02     268  914.19
   277.4  916.45   286.7  919.68     296  923.46   324.1  935.59   333.4  940.03
#Mann= 3 , 0 , 0
       0     .06       0    86.7    .045       0    96.3     .06       0
Bank Sta=86.7,96.3
XS Rating Curve= 0 ,0
Exp/Cntr=0.3,0.1

Type RM Length L Ch R = 1 ,2054.9  ,79.3,82.6,85.5
XS GIS Cut Line= 3
     1639764.611      278285.652     1639820.139      278048.693
     1639747.528      277950.822
#Sta/Elev= 30
       0     930    19.5  922.64    29.2  918.81    38.9  914.84    48.7  910.65
    58.4  906.02    68.2  900.44    77.9  894.67    87.6  891.42    97.4  891.19
   107.1   891.5   116.8  891.73     146  892.15   175.2  892.46     185  892.82
   194.7  893.84   204.4  895.24   223.9  897.88   233.6  899.05   252.8  900.92
   262.1  901.72   271.5   902.9   280.9  904.61   290.2  906.67     309  911.12
   318.4  913.65   327.8  916.49   346.5  922.85   355.9  926.28   365.2  929.99
#Mann= 3 , 0 , 0
       0     .06       0    87.6    .045       0   107.1     .06       0
Bank Sta=87.6,107.1
XS Rating Curve= 0 ,0
Exp/Cntr=0.3,0.1

Type RM Length L Ch R = 1 ,1972.3  ,71.5,77.4,83.7
XS GIS Cut Line= 3
      1639832.14      278296.861     1639905.378      278114.764
     1639974.822      277910.771
#Sta/Elev= 30
       0     920     9.8  916.48    19.6  912.79    49.1  901.23    58.9  896.52
    68.7   892.1    78.5  889.75    88.3  889.58    98.1  890.03     108  890.41
   176.6  891.78   186.5  892.23   196.3  892.88   206.1  893.35   215.9   893.5
   225.7  893.51   235.4  893.64   245.2   893.9   264.8   894.6   294.2  896.39
     304  897.54   323.6  900.69   333.4  902.52   343.2  904.71     353  906.76
   362.8  908.65   372.6  910.35   382.4  911.79   392.2  913.08   411.8  915.37
#Mann= 3 , 0 , 0
       0     .06       0    78.5    .045       0    98.1     .06       0
Bank Sta=78.5,98.1
XS Rating Curve= 0 ,0
Exp/Cntr=0.3,0.1

Type RM Length L Ch R = 1 ,1894.9  ,107.8,108.8,109.3
XS GIS Cut Line= 2
     1639875.545      278332.196     1640041.429       278106.93
#Sta/Elev= 24
       0  920.01     9.6  916.42    28.9  908.99    38.6  905.38    48.2  901.59
    57.9  896.88    67.5  891.63    77.2  888.28    86.8  888.48    96.5  888.82
   106.1  888.88   115.8  888.26   125.4   887.5     135  886.99   144.7  886.98
   154.4  886.98     164  887.19   183.3  887.98   192.9  888.49   202.6  890.19
   212.2  894.24   221.9  899.11   260.5  919.79   279.8     930
#Mann= 3 , 0 , 0
       0     .06       0    77.2    .045       0    86.8     .06       0
#XS Ineff= 2 , 0
                          100.14          889.02
Permanent Ineff=
       F       F
Bank Sta=77.2,86.8
XS Rating Curve= 0 ,0
Exp/Cntr=0.3,0.1

Type RM Length L Ch R = 1 ,1786.2  ,185.4,172.7,159.9
XS GIS Cut Line= 2
      1639941.01      278419.255     1640134.897      278171.703
#Sta/Elev= 24
       0  930.24     9.8  927.57    19.6  924.39    29.5  920.72      59  908.86
    78.6  900.71    88.4  896.54    98.3  891.62   108.1  887.11  112.22886.2173
   117.9  884.99   127.7  884.68   137.6  884.88   196.5  886.49   206.4  886.97
   216.2  888.77     226  893.55   235.8  899.56   255.5  912.18   265.3   918.3
   275.1  924.17     285  929.74   294.8  934.88   314.4  944.81
#Mann= 3 , 0 , 0
       0     .06       0  112.22    .045       0   127.7     .06       0
Bank Sta=112.22,127.7
XS Rating Curve= 0 ,0
Exp/Cntr=0.3,0.1

Type RM Length L Ch R = 1 ,1613.5  ,159.5,171,182.5
XS GIS Cut Line= 4
     1639982.418      278573.749     1640134.327      278472.837
     1640150.603      278356.735     1640237.409      278215.676
#Sta/Elev= 30
       0  959.44    38.4  943.42      48  939.35      96  918.73   105.6  914.83
   115.2   911.3   124.8  908.21   172.8  895.03   182.4  892.52   201.9  887.92
   211.7  885.22   221.4  882.75   222.1  882.66   231.2  881.55     241   881.8
   260.5  883.11   270.3  883.61   289.8  884.36   309.4  884.92   319.1  886.15
   328.8  889.26   338.6  893.61   348.3  898.16   367.8  907.11   377.6  911.71
   387.3  916.49     397  921.55     436  942.22   445.8  947.34   465.2  957.81
#Mann= 3 , 0 , 0
       0     .06       0   222.1    .045       0     241     .06       0
Bank Sta=222.1,241
XS Rating Curve= 0 ,0
Exp/Cntr=0.3,0.1

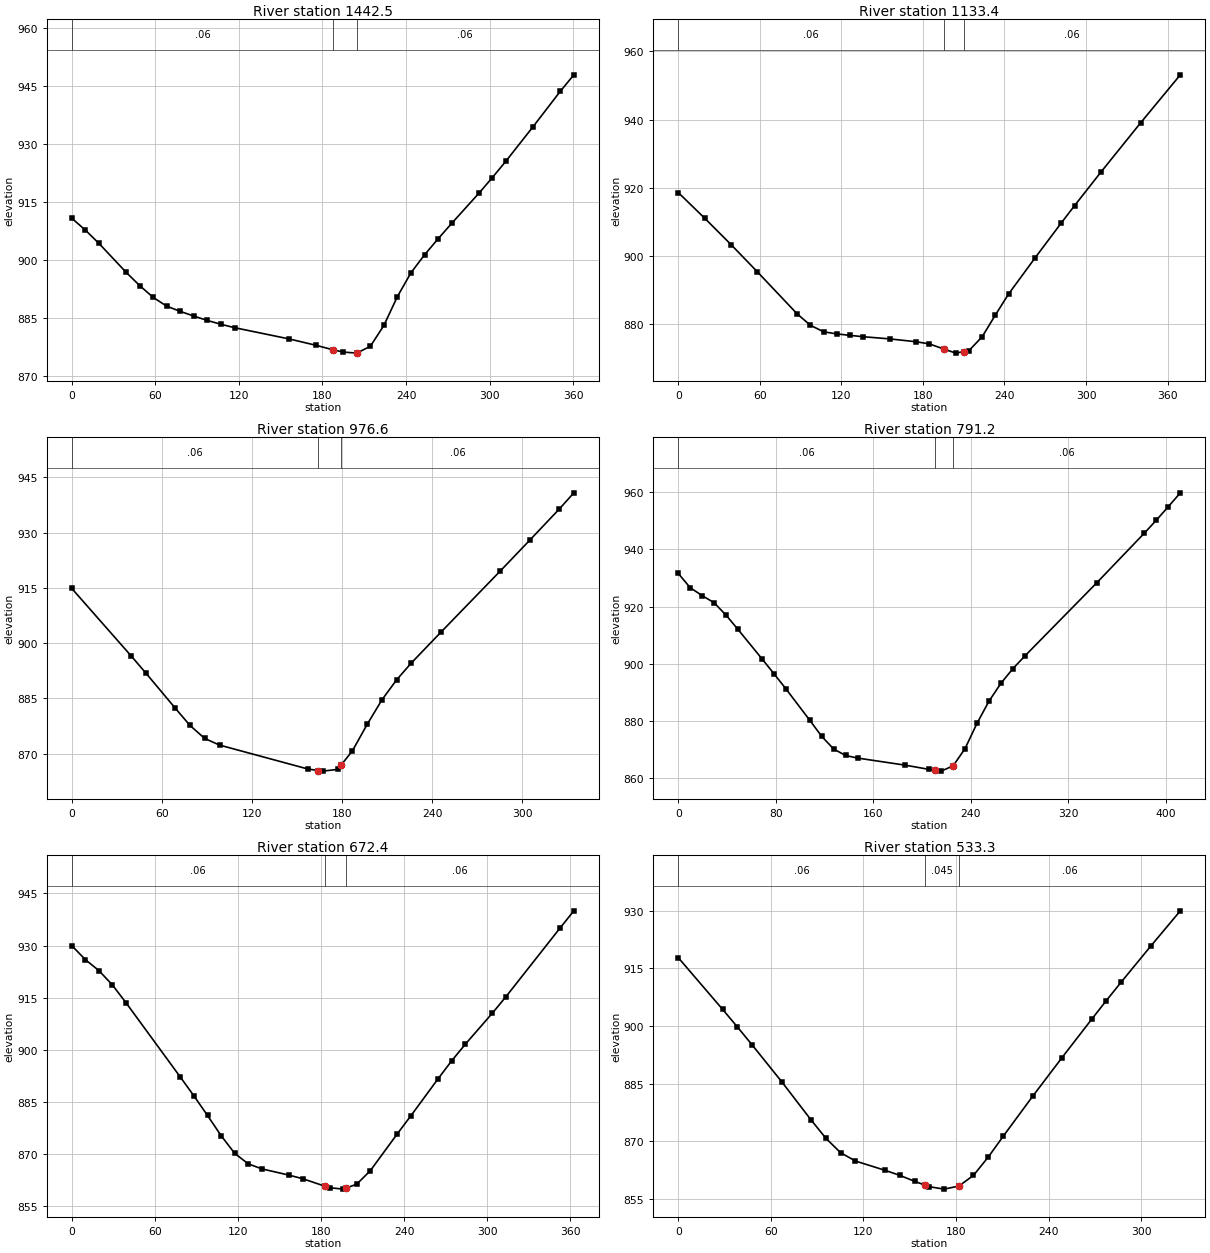
Type RM Length L Ch R = 1 ,1442.5  ,301.6,309.1,316.5
XS GIS Cut Line= 2
     1640177.898      278592.046     1640377.184      278291.621
#Sta/Elev= 30
       0  910.82     9.7  907.77    19.5  904.32      39  896.86    48.7  893.44
    58.5  890.36    68.2   888.1      78  886.75    87.7  885.54    97.4  884.41
   107.2  883.42   116.9  882.55   155.9  879.66   175.4     878   187.7  876.83
   194.9  876.26   204.6  875.98   214.4  877.75   224.1  883.13   233.8  890.58
   243.6  896.76   253.3  901.37   263.1  905.53   272.8   909.5   292.3  917.26
     302  921.32   311.8  925.59   331.3  934.49   350.8  943.61   360.5  947.85
#Mann= 3 , 0 , 0
       0     .06       0   187.7    .045       0   204.6     .06       0
Bank Sta=187.7,204.6
XS Rating Curve= 0 ,0
Exp/Cntr=0.3,0.1

Type RM Length L Ch R = 1 ,1133.4  ,154.5,156.8,159
XS GIS Cut Line= 2
      1640354.67      278756.034     1640647.832      278531.268
#Sta/Elev= 26
       0  918.62    19.4   911.1    38.9  903.32    58.3  895.32    87.5  883.01
    97.2  879.69   106.9  877.76   116.7  877.14   126.4  876.71   136.1  876.31
   155.5  875.68     175  874.84   184.7  874.21   195.4  872.71   204.2   871.5
   210.4  871.97   213.9  872.24   223.6   876.3   233.3  882.66     243  888.82
   262.5  899.42   281.9  909.73   291.6  914.77   311.1  924.66   340.2  939.06
   369.4  953.14
#Mann= 3 , 0 , 0
       0     .06       0   195.4    .045       0   210.4     .06       0
Bank Sta=195.4,210.4
XS Rating Curve= 0 ,0
Exp/Cntr=0.3,0.1

Type RM Length L Ch R = 1 ,976.6   ,184,185.4,186.8
XS GIS Cut Line= 2
     1640455.863       278853.69     1640740.207      278677.612
#Sta/Elev= 22
       0  914.82    39.4  896.58    49.2  891.92    68.9  882.34    78.7  877.65
    88.5  874.12    98.4  872.31   157.4   865.8   164.2  865.41   167.2  865.24
   177.1  865.71   179.2  866.79   186.9  870.74   196.7   877.9   206.6   884.6
   216.4  890.04   226.2  894.61   245.9  902.96   285.3  919.51   304.9  927.86
   324.6  936.33   334.4  940.77
#Mann= 3 , 0 , 0
       0     .06       0   164.2    .045       0   179.2     .06       0
Bank Sta=164.2,179.2
XS Rating Curve= 0 ,0
Exp/Cntr=0.3,0.1

Type RM Length L Ch R = 1 ,791.2   ,115.9,118.8,121.6
XS GIS Cut Line= 2
     1640511.088      279021.395      1640873.94      278826.908
#Sta/Elev= 30
       0  931.61     9.8  926.61    19.6  923.85    29.4  921.36    39.2  917.02
      49  912.02    68.6  901.78    78.4  896.59    88.2   891.3   107.8   880.3
   117.6  874.66   127.4  870.23   137.2  867.95     147  867.05   186.2  864.56
   205.8  863.08   210.7  862.78   215.6  862.48   225.4  864.32   235.2  870.37
     245   879.2   254.8  886.93   264.7  893.24   274.5  898.35   284.3  902.76
   343.1  928.29   382.3  945.72   392.1  950.25   401.9  954.96   411.7  959.78
#Mann= 3 , 0 , 0
       0     .06       0   210.7    .045       0   225.4     .06       0
Bank Sta=210.7,225.4
XS Rating Curve= 0 ,0
Exp/Cntr=0.3,0.1

Type RM Length L Ch R = 1 ,672.4   ,140.6,139.1,137.6
XS GIS Cut Line= 2
     1640556.155      279098.419     1640894.055      278967.209
#Sta/Elev= 29
       0  929.97     9.8  925.94    19.6  922.77    29.4  918.61    39.2  913.48
    78.4  892.07    88.2  886.66      98  881.01   107.8  875.21   117.6   870.1
   127.4  867.07   137.2  865.62   156.8  863.82   166.6   862.8   182.7  860.63
   186.1   860.2   195.9  859.78   197.7  860.04   205.7  861.19   215.5  865.07
   235.1  875.75   244.9  880.96   264.5   891.6   274.3  896.77   284.1  901.53
   303.7  910.52   313.5  915.26   352.7  935.12   362.5     940
#Mann= 3 , 0 , 0
       0     .06       0   182.7    .045       0   197.7     .06       0
Bank Sta=182.7,197.7
XS Rating Curve= 0 ,0
Exp/Cntr=0.3,0.1

Type RM Length L Ch R = 1 ,533.3   ,140.8,139.9,138.9
XS GIS Cut Line= 2
     1640633.459      279226.961     1640928.598      279090.242
#Sta/Elev= 26
       0  917.77    28.7  904.34    38.3  899.76    47.8  895.12      67  885.53
    86.1  875.55    95.7  870.79   105.2  867.05   114.8  864.89   133.9  862.48
   143.5  861.17   153.1  859.62   159.8  858.63   162.6  858.22   172.2  857.58
   181.8  858.37   191.3  861.16   200.9  865.93   210.5   871.3   229.6   881.7
   248.7   891.8   267.9  901.76   277.4  906.62     287  911.41   306.1  920.74
   325.3  929.94
#Mann= 3 , 0 , 0
       0     .06       0   159.8    .045       0   181.8     .06       0
Bank Sta=159.8,181.8
XS Rating Curve= 0 ,0
Exp/Cntr=0.3,0.1

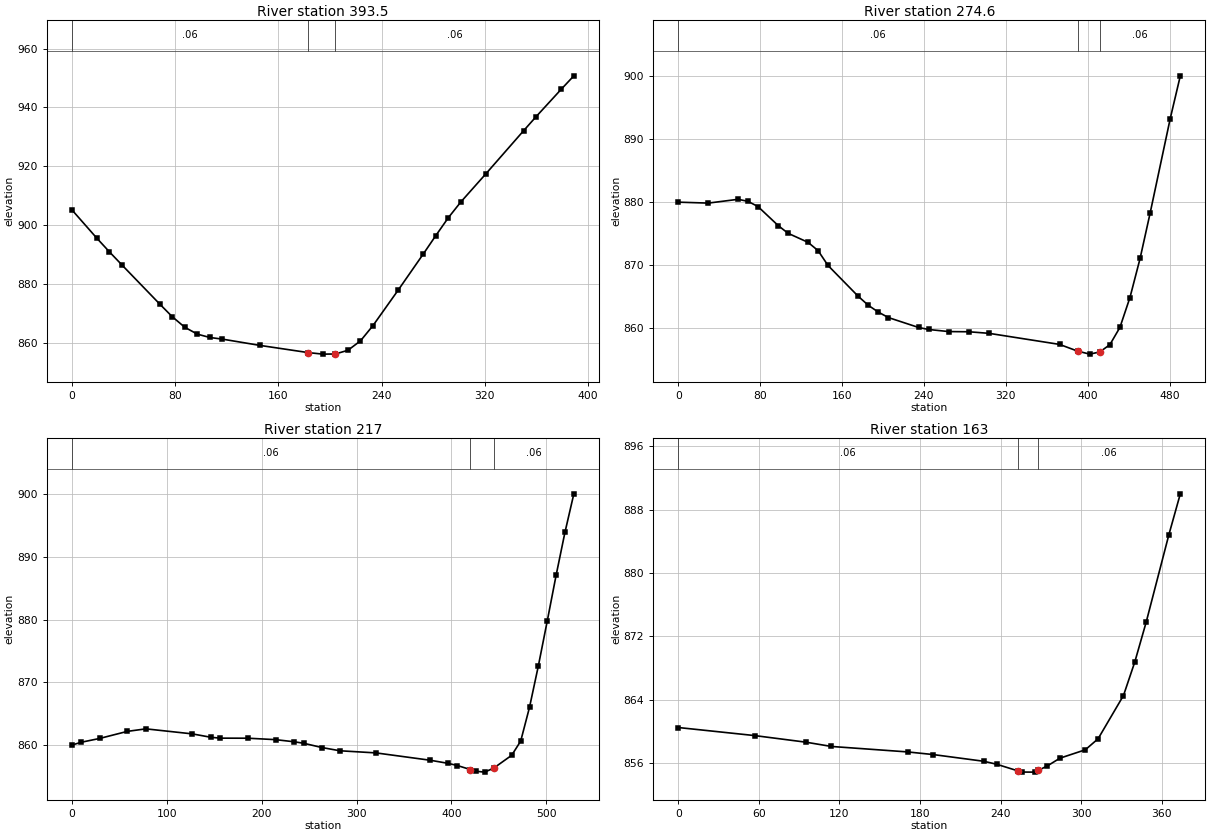
Type RM Length L Ch R = 1 ,393.5   ,116.5,118.9,121.2
XS GIS Cut Line= 2
      1640682.47      279367.041     1641027.149      279186.666
#Sta/Elev= 27
       0   905.2    19.4  895.52    29.2  890.85    38.9   886.4    68.1  873.14
    77.8  868.84    87.5  865.24    97.3  862.88     107  861.75   116.7  861.19
   145.9  859.05   183.2  856.61   194.5  856.09   204.2  856.14     214   857.4
   223.7  860.61   233.4  865.81   252.9  877.86   272.3  890.11     282  896.36
   291.8  902.51   301.5  907.86   320.9  917.43   350.1  932.07   359.8  936.86
   379.3  946.19     389  950.72
#Mann= 3 , 0 , 0
       0     .06       0   183.2    .045       0   204.2     .06       0
Bank Sta=183.2,204.2
XS Rating Curve= 0 ,0
Exp/Cntr=0.3,0.1

Type RM Length L Ch R = 1 ,274.6   ,57.5,57.6,57.7
XS GIS Cut Line= 3
     1640546.008       279477.64     1640691.874      279466.028
     1641011.069      279337.343
#Sta/Elev= 30
       0     880    29.3  879.85    58.5  880.45    68.3  880.12      78  879.29
    97.6   876.3   107.3  875.07   126.8  873.64   136.6  872.33   146.3  869.98
   175.8   865.1   185.7  863.67   195.5  862.59   205.3  861.73   234.8  860.16
   244.7  859.84   264.3  859.51     284  859.48   303.7  859.23   372.5  857.48
   390.1  856.42     402  855.94   411.8  856.28   421.7  857.44   431.5  860.17
   441.3   864.9   451.2  871.09     461  878.26   480.6   893.2   490.5     900
#Mann= 3 , 0 , 0
       0     .06       0   390.1    .045       0   411.8     .06       0
Bank Sta=390.1,411.8
XS Rating Curve= 0 ,0
Exp/Cntr=0.3,0.1

Type RM Length L Ch R = 1 ,217     ,55.7,54,52.4
XS GIS Cut Line= 4
     1640548.477      279535.244     1640796.903      279482.722
     1641000.663      279402.234     1641040.135      279362.555
#Sta/Elev= 30
       0     860     9.8  860.45    29.3  861.06    58.6  862.19    78.1  862.59
     127  861.79   146.5  861.25   156.3  861.11   185.6   861.1   214.8  860.87
   234.4  860.53   244.2   860.3   263.4  859.62   282.5   859.1   320.6  858.76
   377.8  857.59   396.8  857.09   406.3  856.75     420  856.11   425.4  855.85
   434.9   855.7   444.4  856.32   463.5  858.38     473  860.64   482.3  866.03
   491.6  872.61     501  879.78   510.3  887.03   519.6  893.86     529  900.01
#Mann= 3 , 0 , 0
       0     .06       0     420    .045       0   444.4     .06       0
Bank Sta=420,444.4
XS Rating Curve= 0 ,0
Exp/Cntr=0.3,0.1

Type RM Length L Ch R = 1 ,163     ,162.3,163,163.7
XS GIS Cut Line= 4
     1640744.787      279510.381     1640857.667      279526.079
     1641053.815      279432.256     1641063.211      279391.041
#Sta/Elev= 21
       0  860.51      57  859.49      95  858.66     114  858.12   170.7  857.43
   189.6   857.1   227.4  856.25   236.9  855.88   252.8  855.04   255.8  854.89
   265.2  854.88   267.8  855.09   274.7  855.66   284.1  856.64     303   857.7
   312.5  859.09   331.4  864.55   339.8  868.77   348.3  873.81   365.2  884.85
   373.7     890
#Mann= 3 , 0 , 0
       0     .06       0   252.8    .045       0   267.8     .06       0
Bank Sta=252.8,267.8
XS Rating Curve= 0 ,0
Exp/Cntr=0.3,0.1

Chan Stop Cuts=-1
Use User Specified Reach Order=0
Composite Channel Slope=5